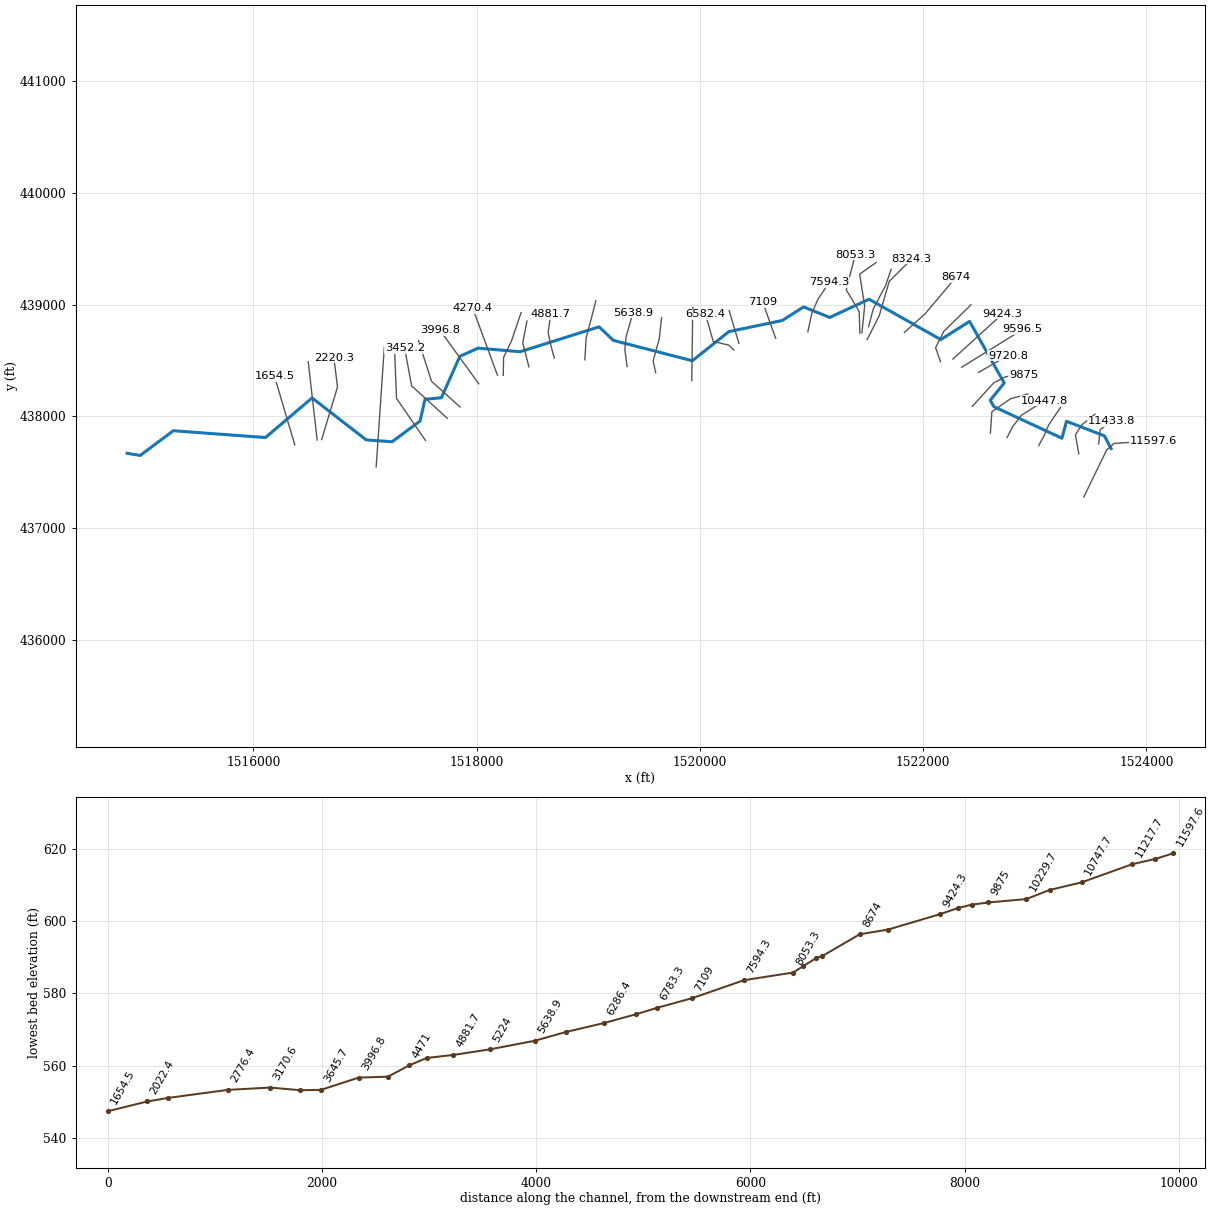
--- QUEENSCR.prj (project) ---

Proj Title=QUEENSCR
Current Plan=p01
Default Exp/Contr=0,0
English Units
Geom File=g01
Flow File=f01
Plan File=p01
BEGIN DESCRIPTION:
END DESCRIPTION:
DSS Export Rating Curves= 0
DSS Export Rating Curve Sorted= 0
DSS Export Volume Flow Curves= 0
DXF OffsetX= 0
DXF OffsetY= 0
DXF ScaleX= 0
DXF ScaleY= 0

--- QUEENSCR.p01 (plan) ---

Plan Title=Floodplain
Program Version=4.00
Geom File=g01
Flow File=f01
K Sum by GR=0
Std Step Tol=0.01
Critical Tol=0.01
Num of Std Step Trials=20
Max Error Tol=0.3
Flow Tol Ratio=0.001
Split Flow NTrial=30
Split Flow Tol=0.02
Split Flow Ratio=0.02
Log Output Level=0
Friction Slope Method=1
Unsteady Friction Slope Method=2
Unsteady Bridges Friction Slope Method=1
Global Log Level=0
CheckData=False
Run HTab=0
Run UNet=0
Run PostProcess=0
UNET Theta=0
UNET Theta Warmup=0
UNET ZTol=0
UNET ZSATol=0
UNET MxIter=0
UNET MaxInSteps=0
UNET DtIC=0
UNET DtMin=0
UNET MaxCRTS=0
UNET WFStab=0
UNET SFStab=0
UNET WFX=0
UNET SFX=0
UNET DSS MLevel=0
UNET DZMax Abort=0
UNET Convert EG Bridges=0
UNET Use Existing IB Tables=0
UNET Froude Limit=0
UNET Froude Power=0
Write IC File=0
Echo Input=False
Echo Output=False
Write Detailed=0

--- QUEENSCR.f01 (steady flow) ---

Flow Title=NFF Regression Equation
Program Version=4.00
Number of Profiles=1
Profile Names=P100yr
River Rch & RM=QUEENSCR,Main      ,11597.6
     314
River Rch & RM=QUEENSCR,Main      ,11433.8
     379
River Rch & RM=QUEENSCR,Main      ,10229.7
     392
River Rch & RM=QUEENSCR,Main      ,8324.3
     435
River Rch & RM=QUEENSCR,Main      ,8053.3
     602
River Rch & RM=QUEENSCR,Main      ,6582.4
     618
River Rch & RM=QUEENSCR,Main      ,6286.4
     692
River Rch & RM=QUEENSCR,Main      ,4471
     738
Boundary for River Rch & Prof#=QUEENSCR,Main      ,1
Up Type=0
Dn Type=3
Dn Slope=0.001828

--- QUEENSCR.g01 (geometry) ---

Geom Title=Geometry
Program Version=4.00

River Reach=QUEENSCR        ,Main
Reach XY= 30
     1523684.262      437711.782     1523624.722      437825.237
      1523284.61       437956.08      1523243.91      437804.249
     1522634.814      438086.248     1522601.474      438144.014
     1522726.687      438298.519     1522416.521      438850.201
     1522158.572       438687.42     1521515.895      439048.406
     1521162.832      438885.394     1520929.577      438979.795
     1520736.289       438857.64     1520260.221      438758.744
     1519933.002      438497.756     1519224.707      438680.279
     1519097.186      438801.362     1518390.005      438578.677
     1518012.642      438610.334     1517849.558      438537.203
      1517684.67      438166.835     1517537.609      438152.413
      1517493.31      437957.853      1517242.36      437772.594
     1517010.784      437789.585     1516526.296      438164.795
     1516108.113      437810.459     1515282.495      437871.385
     1514986.099      437649.861     1514868.909       437669.44

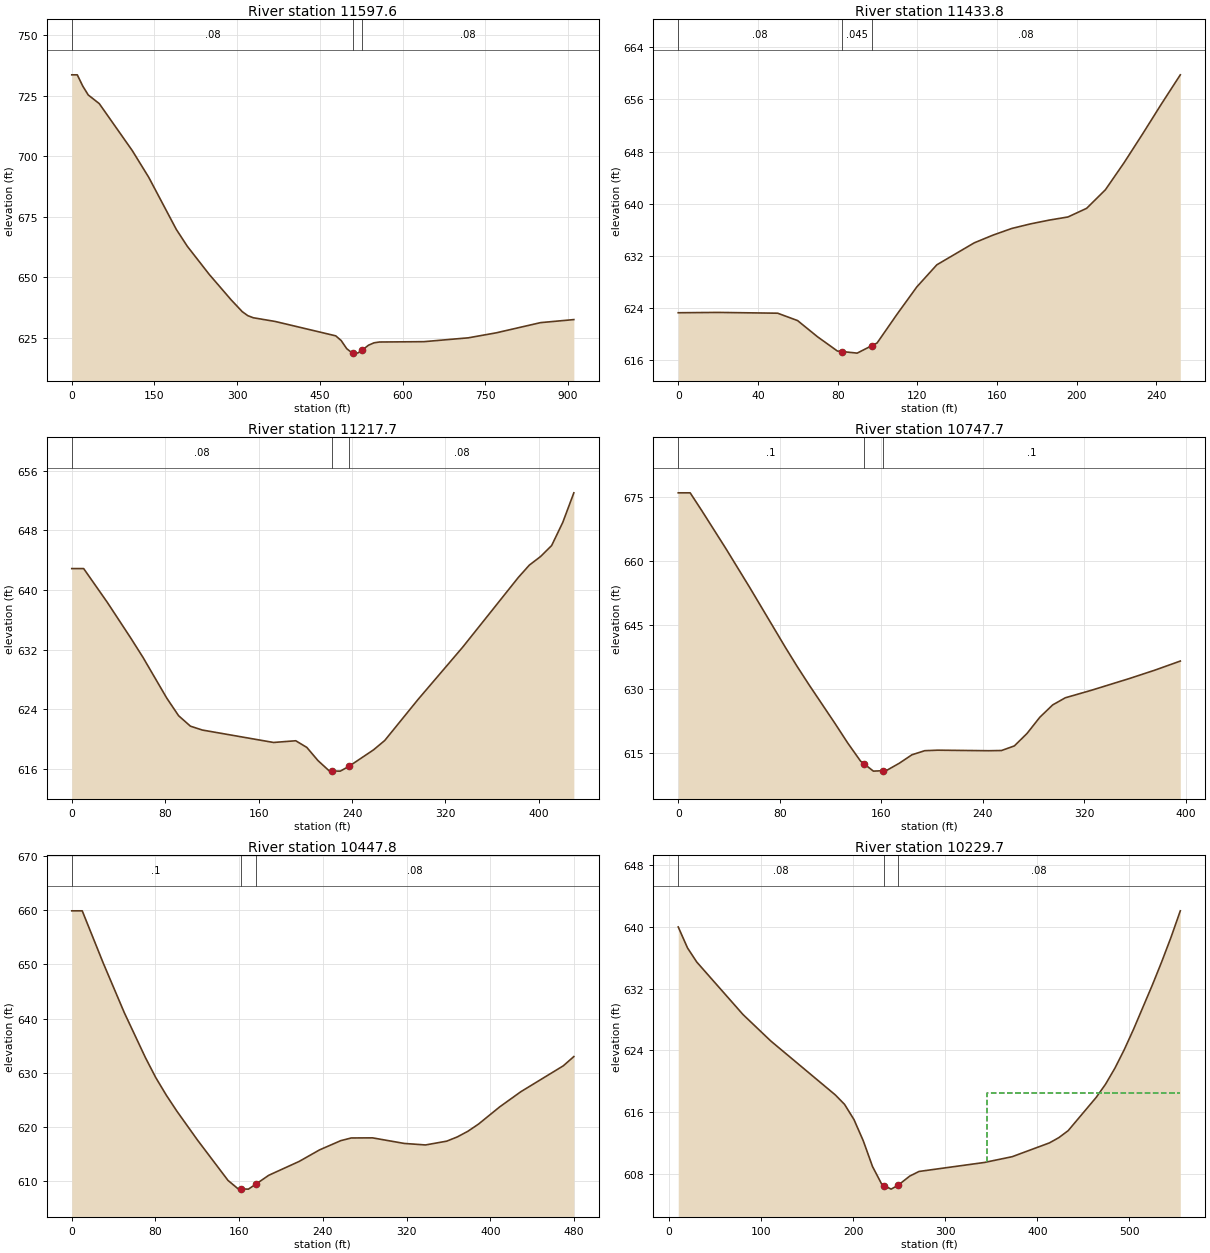
Type RM Length L Ch R = 1 ,11597.6 ,147.1,163.9,179.9
XS GIS Cut Line= 4
     1523439.353      437277.596     1523644.387      437699.313
     1523711.955      437757.562     1524063.774      437780.861
#Sta/Elev= 30
       0  733.57      10  733.57      20   728.9    29.9  725.25    49.9  721.68
   109.7   702.3   139.7  691.22   189.6  669.75   209.5   662.8   249.4  651.14
   289.3   640.6   309.3  635.76   319.3  634.12   329.2  633.26   369.1  631.72
   478.8  625.79   488.7  623.84   498.7   620.5   508.6   618.7     511618.6879
   518.5  618.65     526619.7773   538.3  621.93   548.2   622.9   558.1  623.24
   638.7  623.38   719.3  624.97   769.7  627.02   850.3  631.24   910.7   632.5
#Mann= 3 , 0 , 0
       0     .08       0     511    .045       0     526     .08       0
Bank Sta=511,526
XS Rating Curve= 0 ,0
Exp/Cntr=0.3,0.1

Type RM Length L Ch R = 1 ,11433.8 ,226.4,216.1,205.7
XS GIS Cut Line= 3
     1523572.448      437752.269     1523586.957      437881.235
     1523683.996      437955.606
#Sta/Elev= 25
       0  623.31      20  623.36    49.9  623.24    59.9  622.11    69.9  619.63
    79.9  617.44    82.3617.3624    89.8  617.12    97.3618.2833    99.8  618.67
   109.8  623.07   119.8  627.29   129.8  630.66   148.6  634.03     158  635.21
   167.4  636.23   176.8  636.93   186.2  637.51   195.6  637.99     205  639.32
   214.4  642.16   223.8  646.32   233.2  650.78   242.6  655.35     252  659.78
#Mann= 3 , 0 , 0
       0     .08       0    82.3    .045       0    97.3     .08       0
Bank Sta=82.3,97.3
XS Rating Curve= 0 ,0
Exp/Cntr=0.3,0.1

Type RM Length L Ch R = 1 ,11217.7 ,470.3,470,471.3
XS GIS Cut Line= 4
     1523395.084      437664.365     1523364.795      437834.449
     1523420.713      437922.987      1523539.54      438018.514
#Sta/Elev= 28
       0  642.87    10.2  642.87    30.5  638.32    50.8  633.47      61  630.94
    81.3  625.48    91.5   623.1   101.6   621.7   111.8  621.18   172.8  619.51
   191.8  619.74   201.3  618.84   210.8  617.08   220.4   615.7   222.4615.6898
   228.2  615.66   229.9  615.66   237.4616.3074   258.4  618.52     268  619.78
   296.5  625.29   334.7  632.31   382.3  641.67   391.8  643.34   401.4  644.49
   410.9  645.97   420.4  649.07   429.9  653.05
#Mann= 3 , 0 , 0
       0     .08       0   222.4    .045       0   237.4     .08       0
Bank Sta=222.4,237.4
XS Rating Curve= 0 ,0
Exp/Cntr=0.3,0.1

Type RM Length L Ch R = 1 ,10747.7 ,305.6,299.9,294.2
XS GIS Cut Line= 4
     1523036.275      437738.922     1523085.203       437829.79
     1523124.812      437922.987     1523231.989      438081.422
#Sta/Elev= 30
       0  676.03     9.4  676.03    18.8  671.74    37.5  662.96    56.3  653.82
    84.4  639.76    93.8  635.22   103.2   630.9   123.5  621.89   133.6  617.27
   143.7  613.02   146.3612.4176   153.8  610.67   161.3  610.77     164   610.8
   174.1   612.5   184.2  614.51   194.3  615.47   204.5  615.59   244.7  615.46
   254.8  615.51   264.9  616.59   274.9  619.52     285  623.33   295.1  626.22
   305.1   627.9   325.3  629.63   355.5  632.41   375.6  634.38   395.7  636.52
#Mann= 3 , 0 , 0
       0      .1       0   146.3    .045       0   161.3      .1       0
Bank Sta=146.3,161.3
XS Rating Curve= 0 ,0
Exp/Cntr=0.3,0.1

Type RM Length L Ch R = 1 ,10447.8 ,224.9,218,210.7
XS GIS Cut Line= 4
     1522752.023       437811.15     1522803.282      437909.007
     1522880.169      438009.194     1523085.203       438139.67
#Sta/Elev= 30
       0   659.9      10   659.9    30.1  650.25    50.2  641.11    70.3  632.85
    80.3  629.12    90.4  625.87   100.4  622.95   120.2  617.59   149.3  610.16
     159   608.6   161.3608.5883   168.8  608.55   176.3609.5153   188.2   611.1
   217.3  613.66   236.8  615.79     257  617.49   267.1  617.99   287.4  618.01
   317.8  616.98     338   616.7   358.3   617.4   368.4  618.18   378.5  619.22
   388.7  620.55   408.9  623.72   429.2  626.53   469.7   631.3   479.8  633.01
#Mann= 3 , 0 , 0
       0      .1       0   161.3    .045       0   176.3     .08       0
Bank Sta=161.3,176.3
XS Rating Curve= 0 ,0
Exp/Cntr=0.3,0.1

Type RM Length L Ch R = 1 ,10229.7 ,358.5,354.7,351.5
XS GIS Cut Line= 4
     1522602.908      437850.759     1522616.214      438040.941
     1522781.947      438156.754     1522938.418      438200.249
#Sta/Elev= 30
      10     640    20.1  637.28    30.1  635.46    80.3  628.66   110.4  625.24
   180.6  618.24   190.6  617.02   200.8  615.06   210.9  612.31     221  608.96
   231.1  606.65   233.7 606.493   241.2  606.04   248.7  606.54   261.4  607.73
   271.5  608.33   342.3  609.49   372.6  610.24   413.1  612.03   423.3  612.71
   433.4  613.61   463.9  617.93     474  619.63   484.2  621.71   494.3   624.1
   504.5  626.77   524.8  632.47   534.9  635.46   545.1  638.66   555.2  642.09
#Mann= 3 , 0 , 0
      10     .08       0   233.7    .045       0   248.7     .08       0
#XS Ineff= 2 , 0
                           345.3          618.43
Permanent Ineff=
       F       F
Bank Sta=233.7,248.7
XS Rating Curve= 0 ,0
Exp/Cntr=0.3,0.1

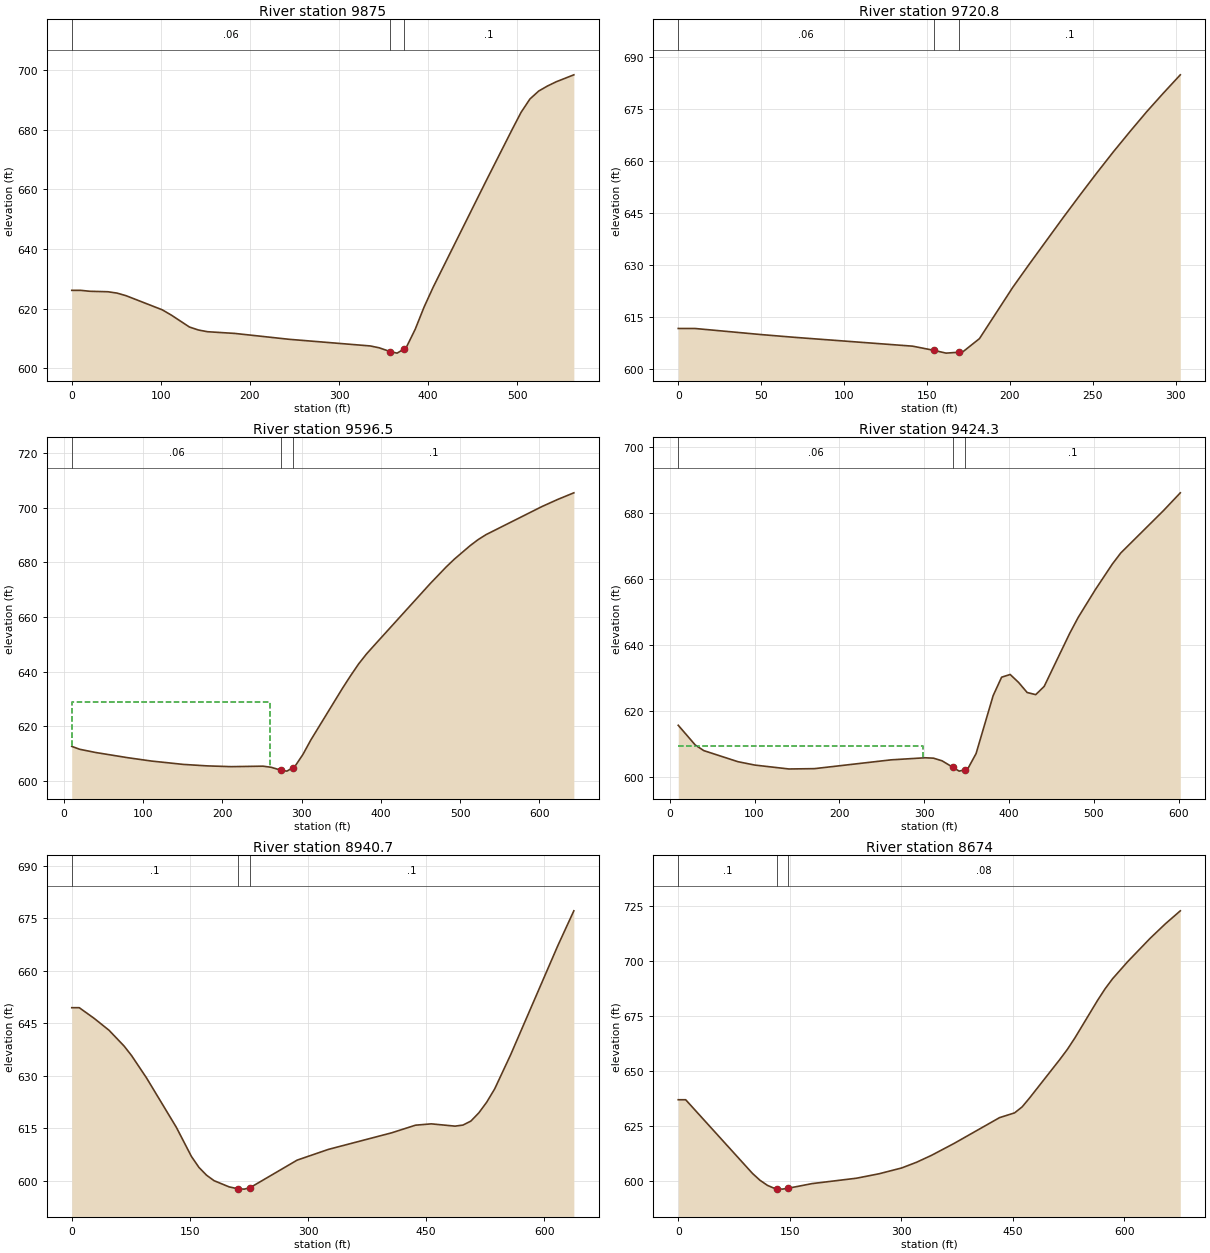
Type RM Length L Ch R = 1 ,9875    ,153.1,154.2,155.3
XS GIS Cut Line= 4
     1522441.269      438090.451     1522633.488      438300.144
     1522741.247       438355.48     1522898.518      438370.042
#Sta/Elev= 30
       0  626.15    10.2  626.15    20.3  625.84    40.6  625.68    50.8  625.23
      61  624.35   101.6  619.62   111.8  617.84   132.1  613.85   142.2  612.85
   152.4  612.28   182.9  611.71   243.8  609.74   334.9  607.51     345  606.89
   357.7605.5755   365.2   605.1   372.7606.4546   375.3  606.93   385.4  613.06
   395.5  620.61   405.6   627.2   464.8  662.71   494.4  680.17   504.3  685.85
   514.2  690.31   524.1  692.99   533.9  694.67   543.8   696.1   563.5  698.42
#Mann= 3 , 0 , 0
       0     .06       0   357.7    .045       0   372.7      .1       0
Bank Sta=357.7,372.7
XS Rating Curve= 0 ,0
Exp/Cntr=0.3,0.1

Type RM Length L Ch R = 1 ,9720.8  ,123.7,124.3,125
XS GIS Cut Line= 2
     1522496.605      438393.342     1522758.722      438544.787
#Sta/Elev= 20
       0  611.61    10.1  611.61    50.5  609.83    70.6  609.04   141.3  606.51
     154605.3166   161.5   604.5     169 604.755   171.5  604.84   181.6  608.68
   201.8  623.56   211.9  630.34   232.1  643.62   242.2   650.1   252.3  656.45
   262.4  662.62   272.5  668.51   282.5  674.19   292.6  679.58   302.7   684.8
#Mann= 3 , 0 , 0
       0     .06       0     154    .045       0     169      .1       0
Bank Sta=154,169
XS Rating Curve= 0 ,0
Exp/Cntr=0.3,0.1

Type RM Length L Ch R = 1 ,9596.5  ,167.8,172.1,176.4
XS GIS Cut Line= 2
     1522345.159       438439.94     1522892.693       438777.78
#Sta/Elev= 30
    10.1  612.67    20.1  611.61    40.2  610.43    80.4  608.54   110.6   607.3
   150.8  606.07   180.9  605.53   211.1  605.25   251.3  605.42   261.4  605.03
     274 603.937   281.5  603.61     289604.8814   291.5  605.31   301.6  609.68
   311.6  614.99   351.8  634.05   361.9  638.58     372  642.88     382  646.55
   392.1  649.81   462.4  672.31   482.5  678.39   492.6  681.19   512.7  686.18
   522.7  688.37   532.8  690.21   603.2  700.47   623.3   703.1   643.4  705.49
#Mann= 3 , 0 , 0
    10.1     .06       0     274    .045       0     289      .1       0
#XS Ineff= 2 , 0
          259.56  628.78
Permanent Ineff=
       F       F
Bank Sta=274,289
XS Rating Curve= 0 ,0
Exp/Cntr=0.3,0.1

Type RM Length L Ch R = 1 ,9424.3  ,473.3,483.6,493
XS GIS Cut Line= 2
     1522266.524      438512.751     1522712.123      438917.576
#Sta/Elev= 30
      10  615.74    30.1  609.77    40.1  608.08    80.3  604.73   100.3   603.7
   140.5  602.52   170.6  602.62   260.9  605.28     301  605.91     311  605.79
   321.1  604.99   333.7603.0382   341.2  601.87   348.7602.3275   351.2  602.48
   361.2  607.19   381.3   624.7   391.3  630.29   401.4  631.11   411.4  628.68
   421.4  625.66   431.5  625.01   441.5  627.51   471.6  643.56   481.6  648.38
   501.7  656.74   521.8   664.5   531.8  667.87     582  680.65     602  686.07
#Mann= 3 , 0 , 0
      10     .06       0   333.7    .045       0   348.7      .1       0
#XS Ineff= 2 , 0
          298.32  609.59
Permanent Ineff=
       F       F
Bank Sta=333.7,348.7
XS Rating Curve= 0 ,0
Exp/Cntr=0.3,0.1

Type RM Length L Ch R = 1 ,8940.7  ,275.1,266.7,258.2
XS GIS Cut Line= 4
     1522155.852      438489.451     1522111.912      438614.727
     1522184.976      438760.306     1522429.619      438999.124
#Sta/Elev= 30
       0  649.42     9.5  649.42    28.4  646.38    47.4  642.96    66.4  638.48
    75.9  635.76    94.8  629.42   132.8  615.27   151.9  606.97   161.5  603.83
   171.1  601.61   180.7  600.04   199.8  598.27   211.5597.7006     219  597.63
   226.5598.0581   286.1   605.9   325.8  608.97   406.3  613.71   436.4  615.88
   456.5  616.26   486.7  615.61   496.8  615.92   506.8  617.06   516.9  619.41
   526.9  622.46     537  626.25   557.1  635.91   617.4  667.25   637.5  677.07
#Mann= 3 , 0 , 0
       0      .1       0   211.5    .045       0   226.5      .1       0
Bank Sta=211.5,226.5
XS Rating Curve= 0 ,0
Exp/Cntr=0.3,0.1

Type RM Length L Ch R = 1 ,8674    ,336.6,349.7,362.6
XS GIS Cut Line= 3
     1521832.574      438751.568     1522018.553      438918.374
     1522292.736      439243.766
#Sta/Elev= 30
       0   636.9      10   636.9    99.9  603.43   109.9  600.35   119.9  598.03
   129.9  596.59   132.4  596.52   139.9  596.31   147.4596.6793   179.9  598.81
   239.8  601.27   270.1  603.28   300.5  605.92   320.7  608.53     341  611.71
   371.4  617.13   432.2  628.78   452.4  630.93   462.6  633.67   472.7  637.76
   513.2  655.16   523.4  659.77   533.5  664.96   563.9  681.96     574  687.22
   584.2  691.84   604.4  699.56   634.8  710.22   655.1  716.75   675.3  722.68
#Mann= 3 , 0 , 0
       0      .1       0   132.4    .045       0   147.4     .08       0
Bank Sta=132.4,147.4
XS Rating Curve= 0 ,0
Exp/Cntr=0.3,0.1

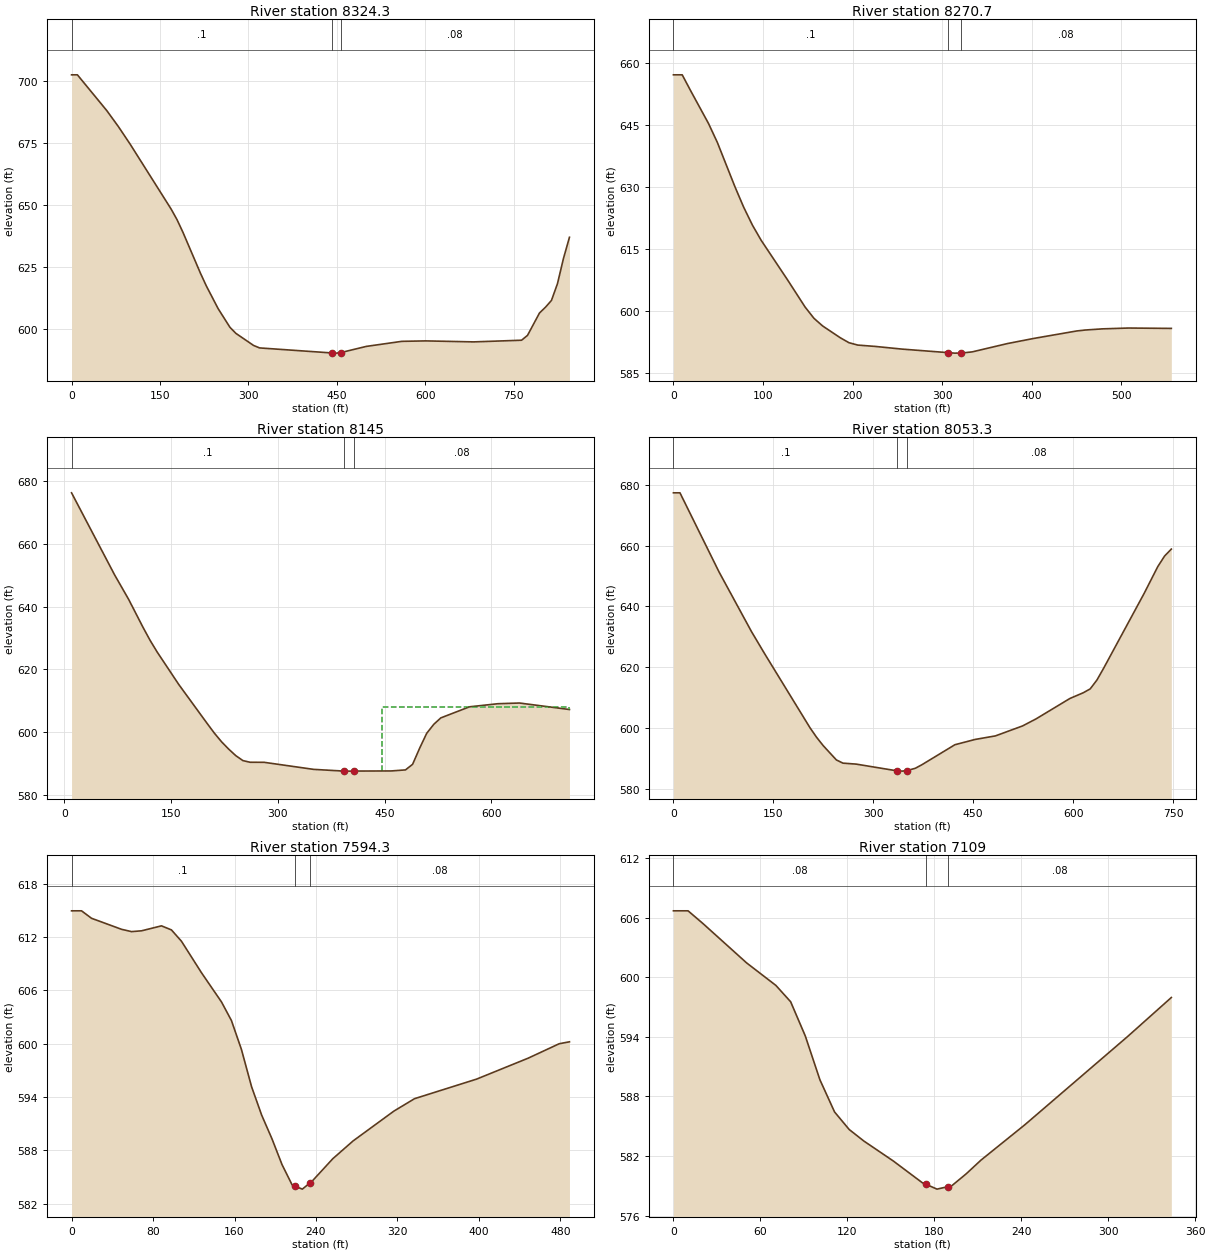
Type RM Length L Ch R = 1 ,8324.3  ,58.2,53.6,49
XS GIS Cut Line= 4
     1521498.738      438687.146     1521606.498      438899.752
     1521696.782      439208.468     1521897.739      439409.424
#Sta/Elev= 30
       0  702.46     9.9  702.46    59.6  688.08    79.5  681.56    99.3  674.53
   168.8  648.36   178.8  644.09   188.7  639.07   218.5  622.51   228.4  617.42
   248.4  608.26   268.5  600.71   278.6  598.25   308.7  593.36   318.8  592.38
   441.9  590.34   449.4  590.28   456.9590.5176   499.7  592.99     560  595.03
   600.6  595.21   681.8  594.81     763  595.48   773.1  597.44   793.4  606.46
   803.6   608.8   813.7  611.53   823.9   618.3     834  628.41   844.2  636.98
#Mann= 3 , 0 , 0
       0      .1       0   441.9    .045       0   456.9     .08       0
Bank Sta=441.9,456.9
XS Rating Curve= 0 ,0
Exp/Cntr=0.3,0.1

Type RM Length L Ch R = 1 ,8270.7  ,114.2,125.7,140.2
XS GIS Cut Line= 4
     1521511.608      438802.157     1521553.993      438963.223
     1521664.196      439171.518     1521713.848       439316.84
#Sta/Elev= 29
       0   657.2     9.8   657.2    19.6  653.19    39.2  645.39      49  640.83
    68.6  630.11    78.4  625.13    88.2  620.77      98  617.08   127.4  607.51
     147  600.92   156.8  598.21   166.5  596.35   186.2  593.49     196  592.28
   205.8  591.71   225.5  591.38   254.9  590.74   306.3589.8824   313.8  589.76
   321.3589.7753   333.5  590.06   372.7  592.07   402.2  593.32   450.2  595.13
   459.8  595.36     479  595.64   507.8  595.84   555.8  595.75
#Mann= 3 , 0 , 0
       0      .1       0   306.3    .045       0   321.3     .08       0
Bank Sta=306.3,321.3
XS Rating Curve= 0 ,0
Exp/Cntr=0.3,0.1

Type RM Length L Ch R = 1 ,8145    ,79.7,91.6,100.6
XS GIS Cut Line= 4
     1521452.268      438748.873     1521476.488      438988.654
     1521431.681      439273.243     1521579.425      439377.391
#Sta/Elev= 30
      10  676.29    70.3   650.2    90.4  642.23   110.5  633.35   120.5  629.18
   130.5  625.44   160.7  615.14   200.8  602.64   210.9  599.57   220.9  596.84
     231  594.49     241   592.4   250.9  590.85   260.9  590.32   280.7   590.3
   350.3  588.05   392.4587.5052     400  587.49   407.4587.5125   459.6  587.55
   479.4  587.88   489.4  589.67   499.3   594.8   509.2  599.55   519.2  602.43
   529.1  604.48   569.3  608.01   609.4     609   639.6  609.22   709.9  607.15
#Mann= 3 , 0 , 0
      10      .1       0   392.4    .045       0   407.4     .08       0
#XS Ineff= 2 , 0
                          446.98          608.04
Permanent Ineff=
       F       F
Bank Sta=392.4,407.4
XS Rating Curve= 0 ,0
Exp/Cntr=0.3,0.1

Type RM Length L Ch R = 1 ,8053.3  ,481.4,459.1,436.7
XS GIS Cut Line= 4
     1521433.574      438742.831     1521427.749      438937.963
     1521311.252      439133.095       1521392.8      439447.635
#Sta/Elev= 30
       0  677.36     9.8  677.36    68.3  651.38   117.1  631.71   136.7  624.47
   205.1  599.99     215  596.86   224.9  594.12   244.6  589.43   254.5  588.38
   274.3  588.06   335.9585.8342   343.4  585.75   350.9 585.947   363.2   586.7
   373.1  587.87   422.5  594.44   452.9  596.18   483.4  597.35     524  600.62
   544.3  602.94   595.1  609.66   615.4  611.57   625.6  612.82   635.7  615.73
   645.9  619.67   706.8  644.34   727.1  653.09   737.3  656.56   747.4  658.84
#Mann= 3 , 0 , 0
       0      .1       0   335.9    .045       0   350.9     .08       0
Bank Sta=335.9,350.9
XS Rating Curve= 0 ,0
Exp/Cntr=0.3,0.1

Type RM Length L Ch R = 1 ,7594.3  ,468.8,485.3,496.5
XS GIS Cut Line= 4
     1520967.588      438757.393     1521002.537      438920.488
     1521057.872      439048.635     1521159.807       439200.08
#Sta/Elev= 30
       0  614.96     9.8  614.96    19.6  614.12    49.1  612.88    58.9  612.62
    68.7  612.71    88.3  613.27    98.1  612.81   107.9  611.54   127.6  607.99
   147.2  604.71     157  602.61   166.8  599.36   176.8  595.15   186.7  591.96
   196.7  589.33   206.7  586.39   216.6  584.11   219.1583.9925   226.6  583.64
   234.1584.3441   236.6  584.58   256.5  587.06   276.5  589.07   316.5  592.42
   336.8  593.82   397.7  596.02   448.4  598.38   478.8     600   488.9  600.22
#Mann= 3 , 0 , 0
       0      .1       0   219.1    .045       0   234.1     .08       0
Bank Sta=219.1,234.1
XS Rating Curve= 0 ,0
Exp/Cntr=0.3,0.1

Type RM Length L Ch R = 1 ,7109    ,326.8,325.7,324.6
XS GIS Cut Line= 2
     1520679.259      438699.145     1520562.762      439022.423
#Sta/Elev= 22
       0  606.72    10.1  606.72    20.2  605.46    50.5  601.47    70.7   599.2
    80.9  597.55      91   594.1   101.1  589.68   111.2  586.44   121.3  584.67
   131.4  583.51   151.6  581.51   171.8   579.3   174.4579.1382   181.9  578.66
   189.4578.9073     192  578.99   202.1  580.21   212.2  581.58   242.6  585.16
   313.3  594.03   343.6  597.98
#Mann= 3 , 0 , 0
       0     .08       0   174.4    .045       0   189.4     .08       0
Bank Sta=174.4,189.4
XS Rating Curve= 0 ,0
Exp/Cntr=0.3,0.1

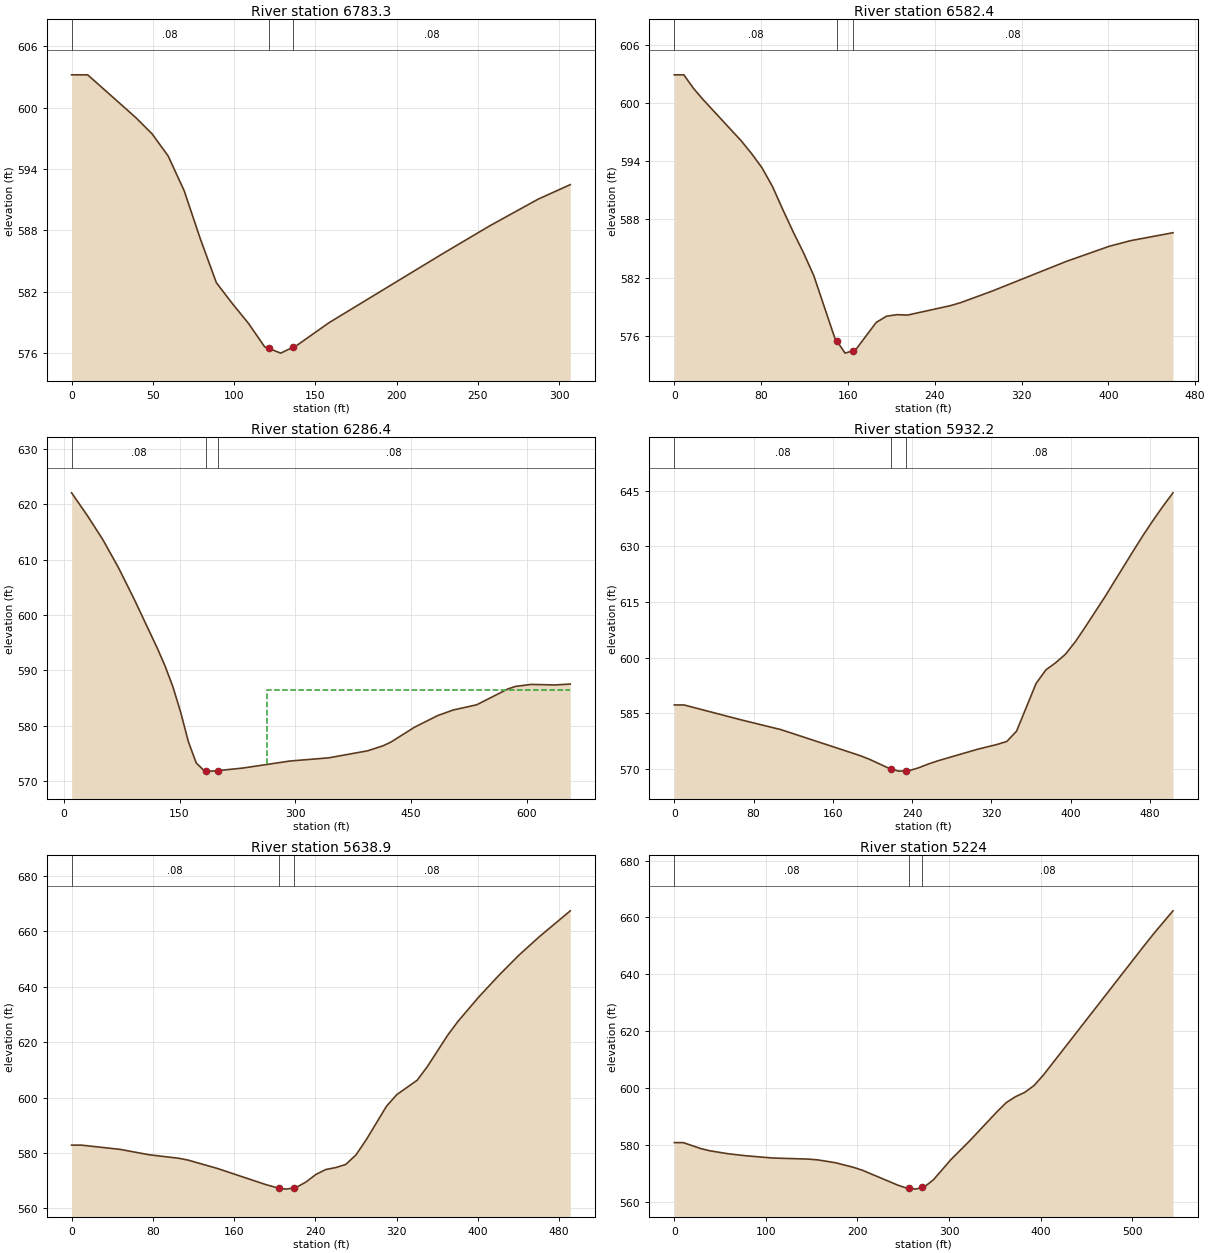
Type RM Length L Ch R = 1 ,6783.3  ,176.9,200.9,224.9
XS GIS Cut Line= 2
     1520350.156      438652.546     1520262.784        438946.7
#Sta/Elev= 20
       0   603.2     9.9   603.2    39.6  599.01    49.5  597.44    59.4  595.28
    69.3  591.87    79.2  587.19    89.1  582.89      99  580.84   108.9  578.91
   118.8  576.63   121.2576.4797   128.7  576.01   136.2576.5782   138.6  576.76
   158.4  578.98   227.7  585.66   257.4  588.45   287.1  591.05   306.9  592.47
#Mann= 3 , 0 , 0
       0     .08       0   121.2    .045       0   136.2     .08       0
Bank Sta=121.2,136.2
XS Rating Curve= 0 ,0
Exp/Cntr=0.3,0.1

Type RM Length L Ch R = 1 ,6582.4  ,326.8,296,265.1
XS GIS Cut Line= 4
     1520303.557      438594.298     1520259.871      438637.984
     1520120.075      438670.021     1520050.177      438914.664
#Sta/Elev= 28
       0  602.93     8.8  602.93    17.7  601.53    26.5  600.38    61.8   596.1
    71.3  594.79    80.9  593.32    90.5   591.4     100  589.02   109.6  586.71
   119.1  584.56   128.7  582.16   147.8   575.8   149.9575.4439   157.4   574.2
   164.9574.4525     167  574.52   186.1  577.37   195.6  578.01   205.2  578.17
     215  578.13   254.1  579.09   263.9  579.41   293.3  580.62   361.8  583.69
   400.9  585.23   420.5  585.81   459.6  586.63
#Mann= 3 , 0 , 0
       0     .08       0   149.9    .045       0   164.9     .08       0
Bank Sta=149.9,164.9
XS Rating Curve= 0 ,0
Exp/Cntr=0.3,0.1

Type RM Length L Ch R = 1 ,6286.4  ,360.1,354.2,348.5
XS GIS Cut Line= 2
     1519927.555      438319.718     1519936.593      438975.824
#Sta/Elev= 30
    10.1  622.05    30.3  617.99    50.5  613.62    70.7  608.57    90.9  602.93
   121.1  594.01   131.2  590.79   141.3  587.05   151.4  582.45   161.5  577.08
   171.6  573.27   181.7   571.9   184.3571.8734   191.8   571.8   199.3571.8817
   232.2  572.36   292.8  573.62   343.2   574.2   393.7  575.47   413.9  576.39
     424  577.06   454.3  579.72   484.6  581.84   504.7  582.84     535  583.78
   575.4  586.64   585.5   587.1   605.7  587.46     636  587.36   656.2  587.52
#Mann= 3 , 0 , 0
    10.1     .08       0   184.3    .045       0   199.3     .08       0
#XS Ineff= 2 , 0
                          263.09          586.38
Permanent Ineff=
       F       F
Bank Sta=184.3,199.3
XS Rating Curve= 0 ,0
Exp/Cntr=0.3,0.1

Type RM Length L Ch R = 1 ,5932.2  ,289.5,293.3,297
XS GIS Cut Line= 4
     1519604.578      438390.429     1519581.279      438495.276
     1519636.615      438696.233     1519657.002      438882.627
#Sta/Elev= 30
       0   587.2     9.8   587.2    68.3  583.12   107.4  580.56   186.8  573.59
   196.7  572.57   216.6  570.11     219569.9224   226.5  569.34     234569.4006
   236.4  569.42   246.4  570.22   256.3  571.25   266.2  572.14   305.9  575.23
   325.7  576.53   335.6  577.35   345.4  580.11   365.2  593.03   375.1  596.68
   384.9  598.59   394.8   600.9   404.7  604.24   414.5  608.12   434.3  616.24
   463.9  629.07   473.7   633.2   483.6  637.16   493.5  640.93   503.3  644.45
#Mann= 3 , 0 , 0
       0     .08       0     219    .045       0     234     .08       0
Bank Sta=219,234
XS Rating Curve= 0 ,0
Exp/Cntr=0.3,0.1

Type RM Length L Ch R = 1 ,5638.9  ,412.8,414.9,416.9
XS GIS Cut Line= 4
     1519348.286      438445.765     1519327.899       438597.21
     1519339.549      438713.707     1519400.709      438926.313
#Sta/Elev= 30
       0   582.8     9.6   582.8    47.8  581.26    76.4  579.31   105.1  578.07
   114.6   577.4   143.3   574.4   191.8  568.48   203.8567.2641   211.4   566.9
   218.8567.3425   221.1  567.48   230.9  569.49   240.6  572.21   250.4  573.99
   260.1  574.69   269.9   575.8   279.9  579.18     290  584.64   310.1  596.83
   320.2  601.02   340.3  606.23   350.3  611.13   370.4  622.52   380.5  627.49
   400.6  636.14   420.7   644.1   440.8  651.51     461   658.2   491.1  667.44
#Mann= 3 , 0 , 0
       0     .08       0   203.8    .045       0   218.8     .08       0
Bank Sta=203.8,218.8
XS Rating Curve= 0 ,0
Exp/Cntr=0.3,0.1

Type RM Length L Ch R = 1 ,5224    ,337.3,342.3,347.4
XS GIS Cut Line= 3
     1518969.672      438506.926     1518981.322      438702.057
     1519068.694      439034.072
#Sta/Elev= 30
       0  580.89     9.8  580.89    29.3  578.76    39.1  578.01    58.6  576.99
    78.2  576.27   107.5  575.48   146.6   575.1   156.4  574.84   175.9  573.83
   195.5  572.22   205.2  571.21     244  565.96   253.7  564.91   255.9564.8289
   263.4  564.55   270.9565.1685   273.1  565.35   282.9  567.82   302.3  575.01
   322.1  581.38   352.4  591.75   362.5  594.96   372.6  597.04   382.8  598.56
   392.9  600.99     403  604.63   514.2  650.57   524.3  654.63   544.5  662.34
#Mann= 3 , 0 , 0
       0     .08       0   255.9    .045       0   270.9     .08       0
Bank Sta=255.9,270.9
XS Rating Curve= 0 ,0
Exp/Cntr=0.3,0.1

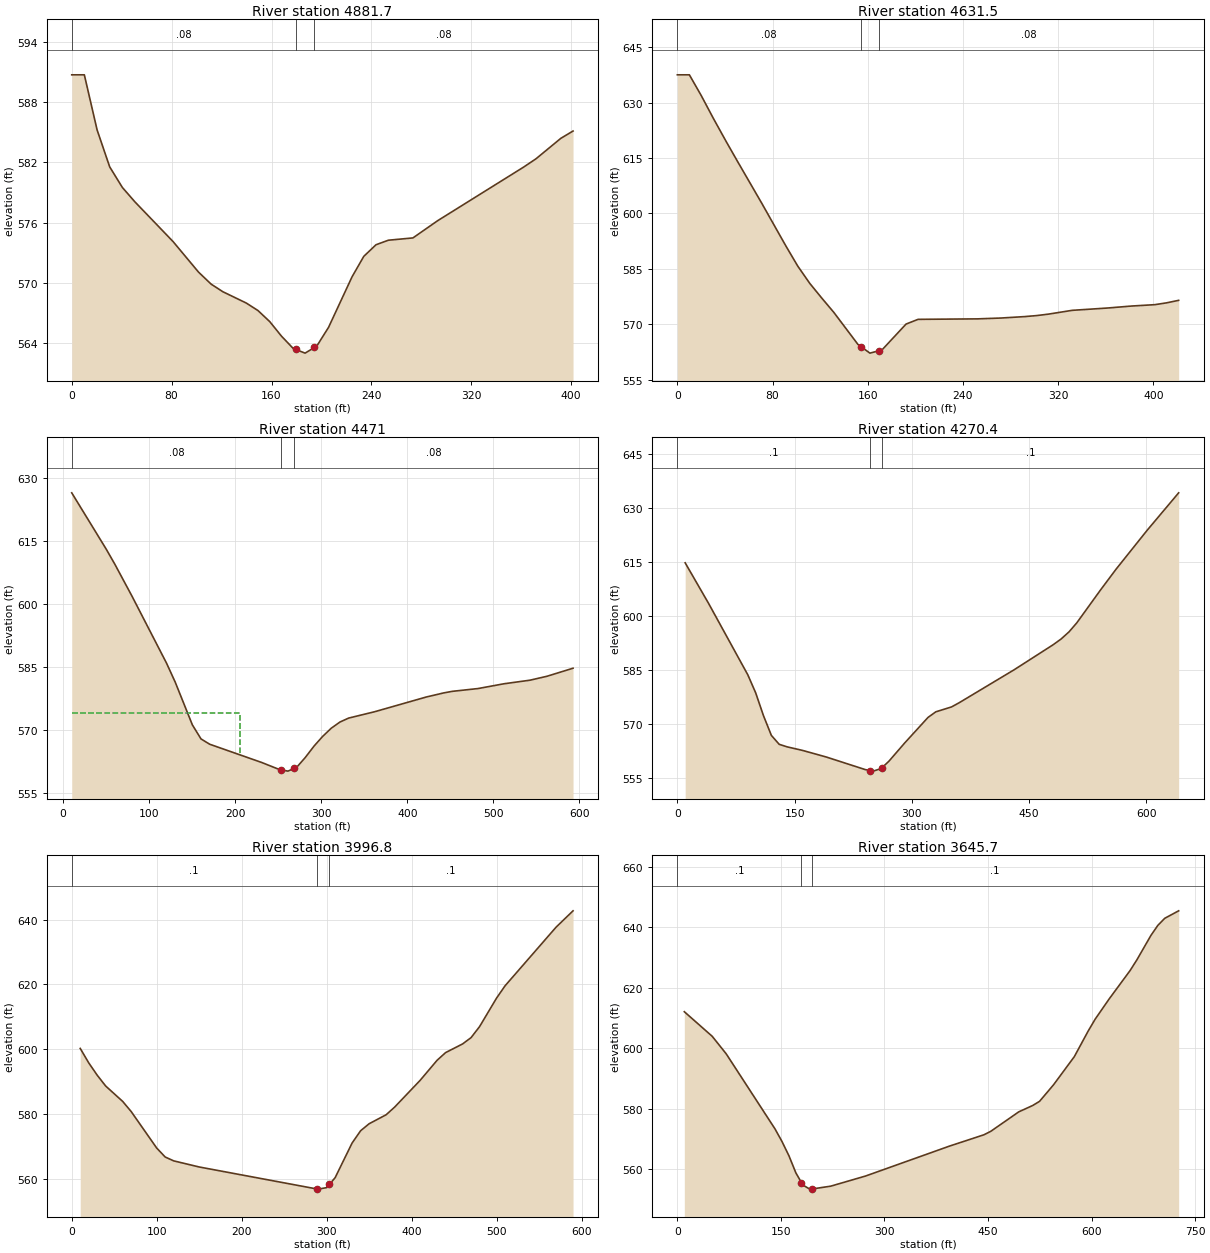
Type RM Length L Ch R = 1 ,4881.7  ,249.7,250.2,250.8
XS GIS Cut Line= 4
     1518695.905      438521.488     1518666.781      438629.247
     1518640.569      438748.656     1518663.869      438914.664
#Sta/Elev= 30
       0  590.73    10.1  590.73    20.3  585.25    30.4  581.56    40.6   579.5
    50.7  578.06    81.2  574.11   101.5  571.08   111.6  569.88     121  569.12
   139.8  567.99   149.2  567.24   158.6  566.14     168  564.69   177.5  563.45
   179.4563.3629   186.9     563   194.4563.5625   196.3  563.71   205.7  565.57
   224.5   570.6   233.9  572.64   243.7   573.8   253.6  574.25   273.3  574.48
     293  576.19   362.1  581.55   371.9  582.37   391.7   584.4   401.5  585.13
#Mann= 3 , 0 , 0
       0     .08       0   179.4    .045       0   194.4     .08       0
Bank Sta=179.4,194.4
XS Rating Curve= 0 ,0
Exp/Cntr=0.3,0.1

Type RM Length L Ch R = 1 ,4631.5  ,176.2,160.4,144.6
XS GIS Cut Line= 3
     1518468.737      438442.853     1518413.401      438658.371
     1518451.262      438853.503
#Sta/Elev= 30
       0  637.55    10.1  637.55    20.2  631.86    30.3  625.73    40.5  619.79
    50.6  614.08    70.8  602.84      91  591.31   101.1  585.78   111.3  581.05
   121.4  577.06   131.5   573.2   151.7  564.55   154.3563.9359   161.8  562.16
   169.3562.7838   171.9     563   192.2  570.03   202.3  571.31   252.3  571.44
   272.2  571.67   292.1  572.06     302  572.33     312  572.73   331.8  573.75
   361.6  574.38   381.5  574.91   401.4  575.29   411.3  575.79   421.3  576.46
#Mann= 3 , 0 , 0
       0     .08       0   154.3    .045       0   169.3     .08       0
Bank Sta=154.3,169.3
XS Rating Curve= 0 ,0
Exp/Cntr=0.3,0.1

Type RM Length L Ch R = 1 ,4471    ,182.4,200.6,218.9
XS GIS Cut Line= 4
     1518238.656       438367.13     1518241.569      438527.313
     1518311.467      438672.933     1518398.839      438929.226
#Sta/Elev= 30
      10  626.56    50.1  613.11    60.1  609.52    80.1  601.87   120.2  585.89
   130.2   581.4   150.2  571.17   160.2  567.83   170.3  566.56   230.9  562.19
   251.1  560.54   253.7560.4346   261.2  560.14   268.7560.8028   271.3  561.03
   281.4   563.4   291.5   566.1   301.5  568.41   311.6  570.39   321.7  571.86
   331.8   572.8   361.9  574.31     422  577.83   442.1   578.8   452.1  579.18
   482.2  579.85   512.3  580.99   542.4  581.84   562.4  582.79   592.5   584.7
#Mann= 3 , 0 , 0
      10     .08       0   253.7    .045       0   268.7     .08       0
#XS Ineff= 2 , 0
          205.37  573.95
Permanent Ineff=
       F       F
Bank Sta=253.7,268.7
XS Rating Curve= 0 ,0
Exp/Cntr=0.3,0.1

Type RM Length L Ch R = 1 ,4270.4  ,267.5,273.6,279.7
XS GIS Cut Line= 2
     1518186.846      438368.457     1517964.427      438970.081
#Sta/Elev= 30
      10  614.85    40.1  603.53    90.2  583.73   100.2  578.75   110.2   572.4
   120.3  566.92   130.3  564.45   140.3  563.75   160.4  562.74   190.4  560.93
   240.5  557.42   246.8  557.16   250.6     557   260.6   557.7   261.8  557.94
   270.6  559.73   290.6  564.75   320.7  571.91   330.7  573.47   350.8  574.83
   360.8  576.02     431  585.16   481.1  592.14   491.1  593.71   501.1  595.67
   511.1  598.19   541.2  607.24   561.2  613.05   601.3  623.94   641.4  634.29
#Mann= 3 , 0 , 0
       0      .1       0   246.8    .045       0   261.8      .1       0
Bank Sta=246.8,261.8
XS Rating Curve= 0 ,0
Exp/Cntr=0.3,0.1

Type RM Length L Ch R = 1 ,3996.8  ,346.1,351.1,355.7
XS GIS Cut Line= 2
     1518019.121      438291.886     1517672.731       438769.54
#Sta/Elev= 30
      10  600.19      20  595.73      30  591.91      40  588.56      60  583.81
      70  580.68     100  569.42     110  566.65     120  565.46     150  563.57
   288.3  556.79     290  556.73     300  557.19   303.3   558.2     310  560.26
     330  570.98     340  574.76     350  576.92     370  579.69     380  582.05
     410  590.31     430  596.52     440  598.89     460  601.57     470  603.52
     480  606.92     500  615.73     510  619.52     570  637.62     590  642.68
#Mann= 3 , 0 , 0
       0      .1       0   288.3    .045       0   303.3      .1       0
Bank Sta=288.3,303.3
XS Rating Curve= 0 ,0
Exp/Cntr=0.3,0.1

Type RM Length L Ch R = 1 ,3645.7  ,193.1,193.5,193.7
XS GIS Cut Line= 3
     1517851.395      438084.053     1517596.161      438313.764
     1517479.482      438678.384
#Sta/Elev= 30
    10.1  612.09    50.5  603.95    70.7  598.17   141.4  573.32   151.5  569.16
   161.6  564.43   171.7  558.74   179.7  555.55   181.8  554.72   191.9  553.36
   194.7  553.39   222.2  554.34   272.7   557.7   393.8  567.57   444.1  571.35
   454.2  572.52   494.5  578.93   514.7  581.04   524.7  582.42   544.9  587.88
   575.1  597.23   595.2  605.72   605.3  609.64   625.5  616.31   655.7  625.67
   665.8   629.3   685.9   637.3     696  640.66   706.1  643.02   726.2  645.49
#Mann= 3 , 0 , 0
       0      .1       0   179.7    .045       0   194.7      .1       0
Bank Sta=179.7,194.7
XS Rating Curve= 0 ,0
Exp/Cntr=0.3,0.1

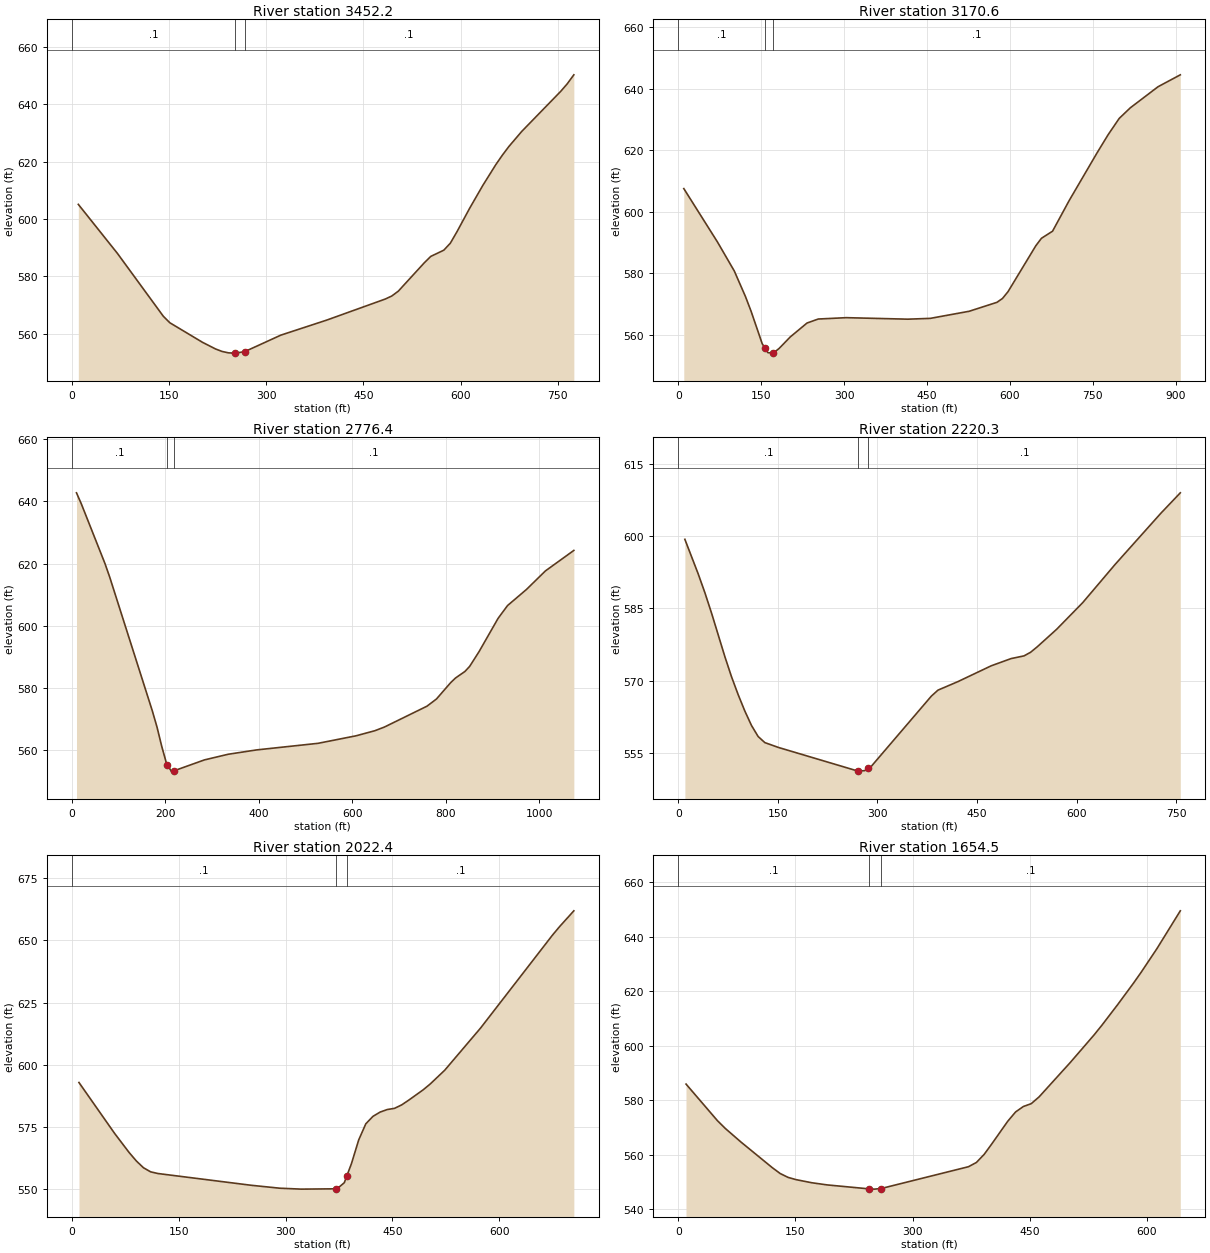
Type RM Length L Ch R = 1 ,3452.2  ,286,281.6,277.3
XS GIS Cut Line= 3
     1517738.363      437981.959     1517417.496      438273.655
     1517355.511      438609.107
#Sta/Elev= 30
    10.1  605.15    70.6     588   141.2  566.14   151.3  563.85   201.7  557.03
   221.9   554.7   231.9  553.84     242  553.34   251.6  553.26   252.1  553.25
   266.6  553.74   322.7  559.53   393.3  564.76   483.8  572.12   493.8  573.17
   503.9  574.86     544  584.76     554  586.99   574.1  589.16   584.1  591.57
   594.2   595.5   614.2  603.86   634.3  611.75   654.4  619.01   664.4  622.28
   674.4  625.29   694.5  630.62   754.7  644.61   764.7  647.23   774.8  650.34
#Mann= 3 , 0 , 0
       0      .1       0   251.6    .045       0   266.6      .1       0
Bank Sta=251.6,266.6
XS Rating Curve= 0 ,0
Exp/Cntr=0.3,0.1

Type RM Length L Ch R = 1 ,3170.6  ,409.2,394.2,379.1
XS GIS Cut Line= 3
     1517541.467      437785.064     1517282.587      438160.623
     1517264.356      438612.753
#Sta/Elev= 30
    10.1  607.49      71  590.13   101.4  580.72   121.6  572.42   131.8  567.63
     152  557.04   156.9  555.65   162.2  554.15   171.9  553.99   182.5   555.5
   202.7  559.25   233.1  563.78   253.4  565.08   304.1  565.52   415.6  565.03
   456.1  565.29   526.5   567.6   576.8  570.51   586.9  571.78   596.9     574
   647.2  588.93   657.3  591.33   677.4  593.64   707.5  603.61   757.8  619.07
   777.9  624.99     798  630.31   818.1  633.76   868.4  640.63   908.6  644.49
#Mann= 3 , 0 , 0
       0      .1       0   156.9    .045       0   171.9      .1       0
Bank Sta=156.9,171.9
XS Rating Curve= 0 ,0
Exp/Cntr=0.3,0.1

Type RM Length L Ch R = 1 ,2776.4  ,561.2,556.2,547.8
XS GIS Cut Line= 2
     1517100.276       437548.06     1517173.201      438620.045
#Sta/Elev= 30
    10.1  642.74    20.3  639.25      71  620.05    81.1  615.72   172.3  572.75
   182.5  567.46   192.6  561.27   202.7  555.84   204.5   555.4   212.9  553.35
   219.5  553.49   283.8  556.95   334.5  558.76   395.3  560.16   527.1  562.28
   608.2  564.69   648.7  566.33     669   567.5   760.2  574.21   780.5  576.52
   810.9  581.77   821.1  583.24   841.3  585.35   851.5  586.99   871.7  591.74
   912.3   602.4   932.6  606.53   973.1   611.7  1013.6  617.65  1074.5  624.24
#Mann= 3 , 0 , 0
       0      .1       0   204.5    .045       0   219.5      .1       0
Bank Sta=204.5,219.5
XS Rating Curve= 0 ,0
Exp/Cntr=0.3,0.1

Type RM Length L Ch R = 1 ,2220.3  ,189,197.9,206.8
XS GIS Cut Line= 3
     1516611.685      437792.356     1516753.887      438262.717
     1516721.071      438525.244
#Sta/Elev= 30
      10   599.4    30.1  592.19    40.1   588.3    50.1  584.07    70.2  574.98
    80.2   570.8    90.3  567.04   100.3  563.65   110.3  560.65   120.3  558.35
   130.4  557.08   150.4  556.09   270.8  551.14   271.1  551.15   280.8  551.24
   286.1  551.72   290.8  552.15   381.1  566.75   391.1     568   421.2  569.78
   471.3  573.07   501.2  574.57   520.8  575.14   530.6  575.89   540.4     577
   569.8  580.67     609  586.21     658   594.2   726.6  604.81     756  609.08
#Mann= 3 , 0 , 0
       0      .1       0   271.1    .045       0   286.1      .1       0
Bank Sta=271.1,286.1
XS Rating Curve= 0 ,0
Exp/Cntr=0.3,0.1

Type RM Length L Ch R = 1 ,2022.4  ,364.5,367.9,368.1
XS GIS Cut Line= 2
     1516571.576       437788.71      1516491.36      438488.782
#Sta/Elev= 30
    10.1  592.95    60.4  572.41    80.5  564.85    90.6  561.46   100.7  558.71
   110.7  557.08   120.8  556.41   251.7  551.69   291.9  550.51   322.1  550.14
   371.1  550.27   372.5  550.29   382.5  552.72   386.1  555.46   392.6  560.42
   402.7  569.86   412.7  576.36   422.8  579.37   432.9  581.09   442.9   582.1
     453  582.57   463.1  583.97   473.1  585.89   493.3  590.03   503.3   592.4
   523.5  597.89   573.8  614.82   674.5  652.05   684.5  655.48   704.7  661.88
#Mann= 3 , 0 , 0
       0      .1       0   371.1    .045       0   386.1      .1       0
Bank Sta=371.1,386.1
XS Rating Curve= 0 ,0
Exp/Cntr=0.3,0.1

Type RM Length L Ch R = 1 ,1654.5  ,437.1,429.5,421.8
XS GIS Cut Line= 2
     1516371.035      437744.956     1516188.725      438361.165
#Sta/Elev= 30
      10  585.96    50.2  572.54    60.2  569.71    80.3  564.71   120.5  555.29
   130.5  553.17   140.6  551.75   150.6  550.94   170.7   549.8   190.8  548.99
   244.6  547.53     251  547.45   259.6  547.66   371.5  555.67   381.6  557.22
   391.6  560.21   401.6  564.14   421.7  572.32   431.8  575.75   441.8  577.75
   451.8  578.78   461.9  581.28     502  593.95   532.2  603.97   542.2  607.52
   562.3  615.05   582.4  622.85   592.4  626.92   612.5  635.54   642.6  649.48
#Mann= 3 , 0 , 0
       0      .1       0   244.6    .045       0   259.6      .1       0
Bank Sta=244.6,259.6
XS Rating Curve= 0 ,0
Exp/Cntr=0.3,0.1