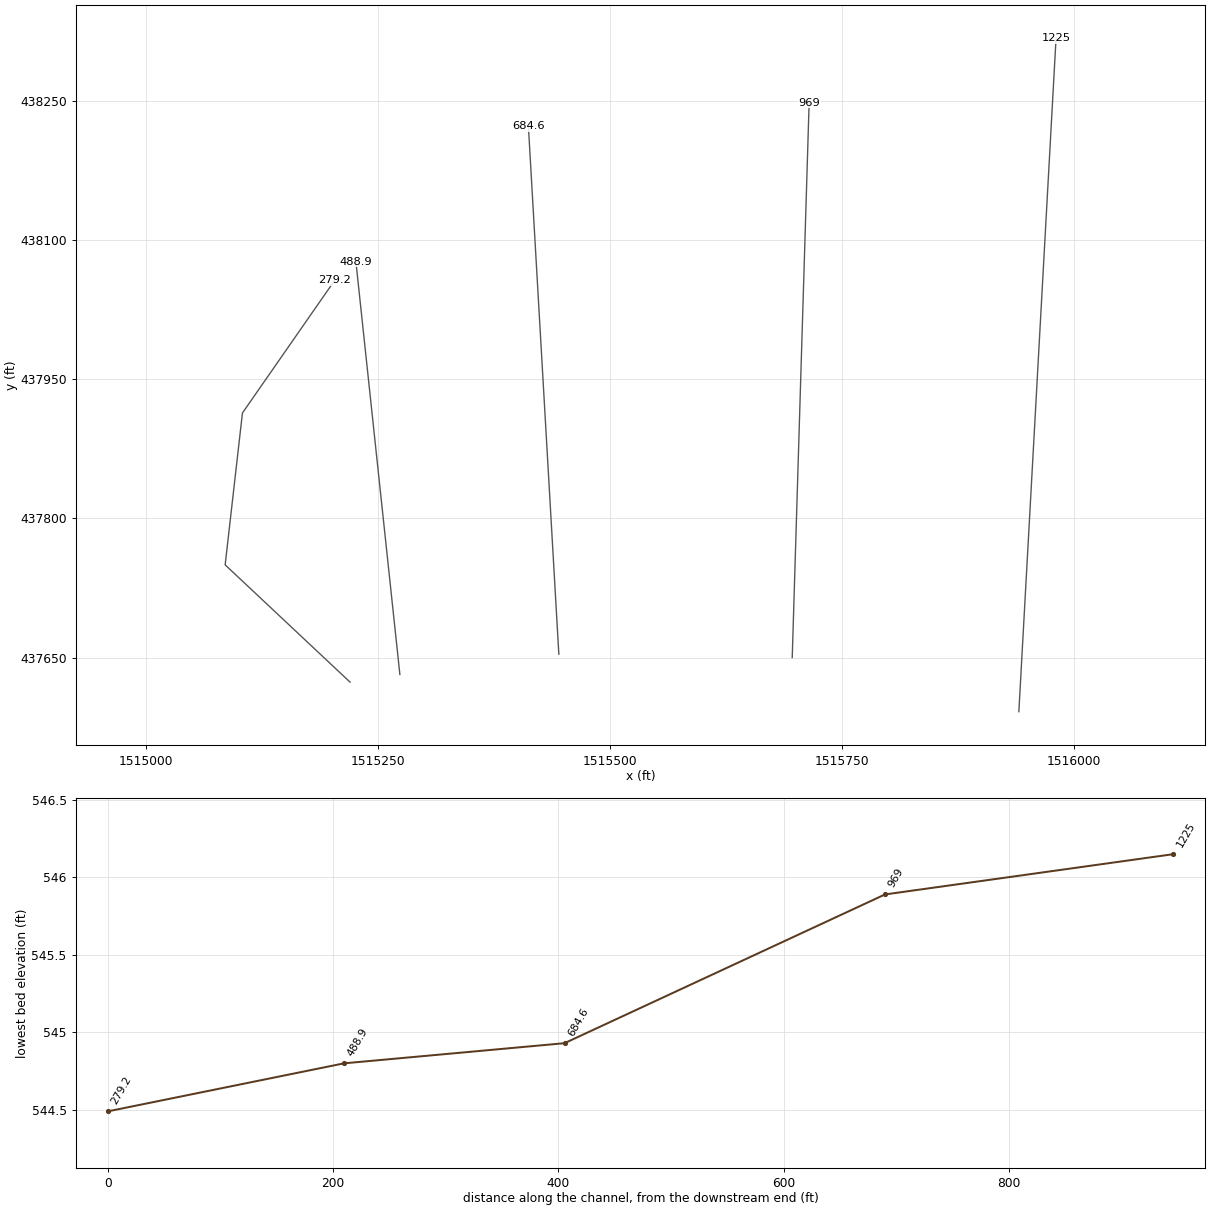
HEC-RAS study QUEENSCR.prj: QUEENSCR

--- QUEENSCR.g01 (geometry) --- (continued)

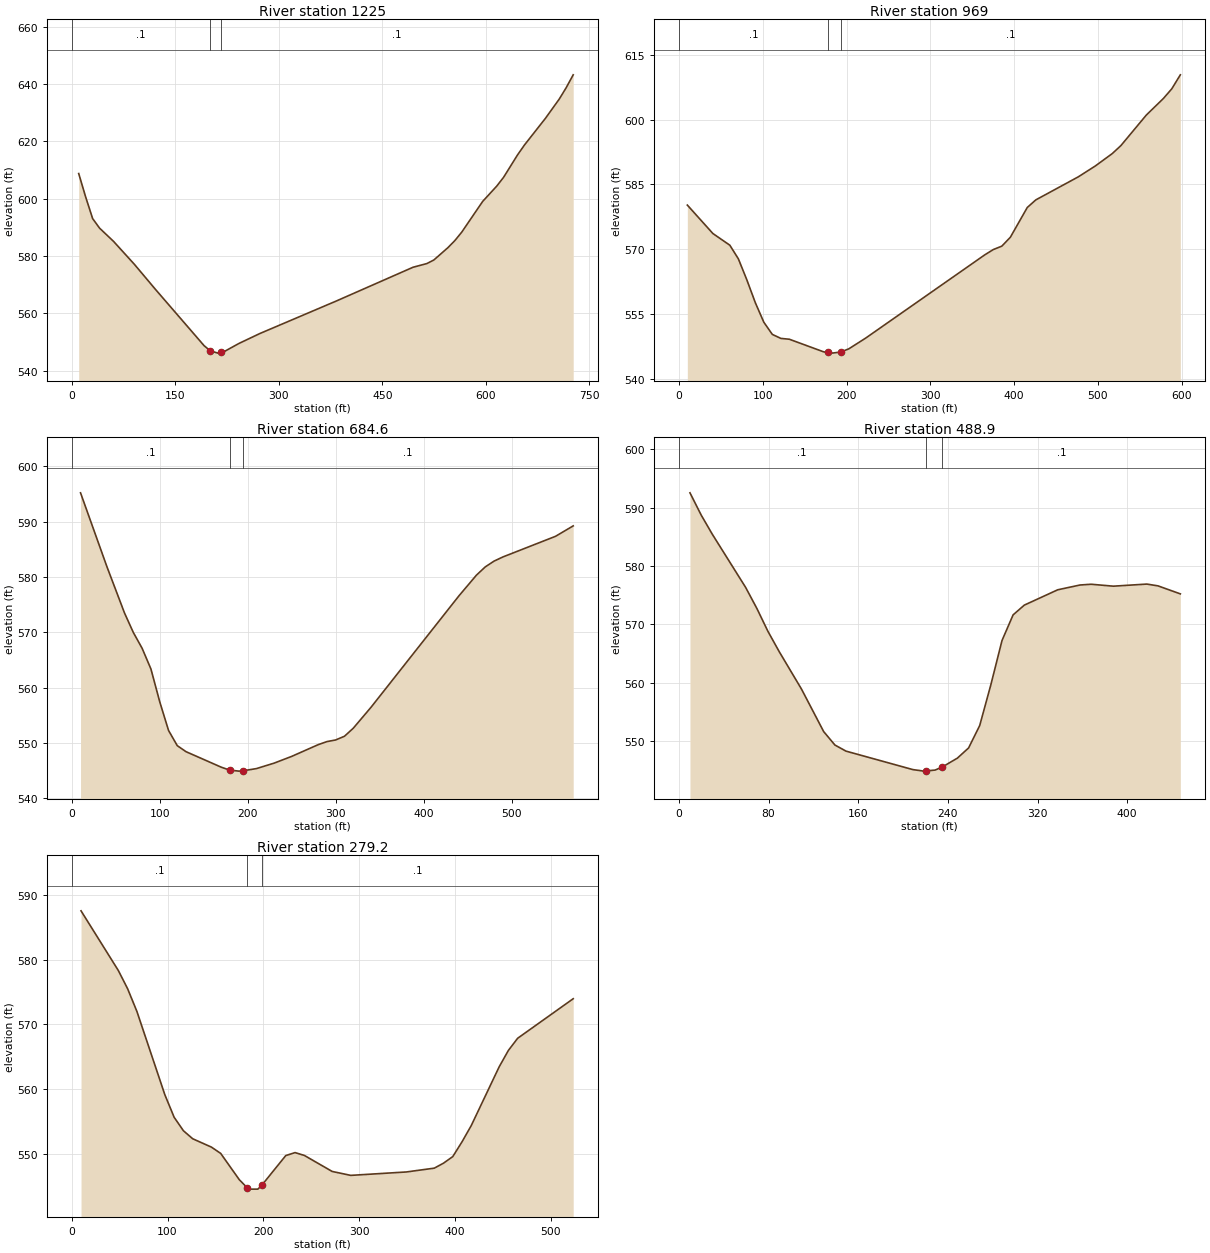
Type RM Length L Ch R = 1 ,1225    ,254.9,256,257.2
XS GIS Cut Line= 2
     1515940.783      437591.815     1515980.891       438317.41
#Sta/Elev= 30
    10.1  608.76    20.2  600.58    30.3  593.05    40.4  589.71    60.6  585.11
    90.8  577.11   121.1  568.44   191.8  548.75   200.9  546.92     212  546.15
   215.9  546.41     222  546.83   242.2  549.51   272.5  552.97   383.5  564.33
   494.6  576.09   514.7  577.38   524.8  578.63     545  582.89   555.1  585.36
   565.2  588.34   595.5  599.04   615.7  604.33   625.8  607.44     646  615.25
   656.1  618.73   686.3  627.96   706.5  634.73   716.6  638.72   726.7  643.18
#Mann= 3 , 0 , 0
       0      .1       0   200.9    .045       0   215.9      .1       0
Bank Sta=200.9,215.9
XS Rating Curve= 0 ,0
Exp/Cntr=0.3,0.1

Type RM Length L Ch R = 1 ,969     ,282.6,284.4,286.2
XS GIS Cut Line= 2
     1515696.487      437650.154     1515714.718      438248.132
#Sta/Elev= 30
    10.1   580.2    40.6  573.61    60.8   570.9      71  567.74    81.1  562.87
    91.3  557.54   101.4  553.04   111.5  550.23   121.7   549.3   131.8  549.11
   172.4  546.21     178  546.04   182.5  545.89     193  546.13   202.8  546.89
   223.1   549.4     365  568.67   375.2   569.9   385.3  570.68   395.5  572.75
   415.7  579.65   425.9  581.41   476.6  586.75   496.9  589.27   517.1  592.14
   527.3  593.97   557.7  601.06     578  604.89   588.1  607.15   598.3  610.39
#Mann= 3 , 0 , 0
       0      .1       0     178    .045       0     193      .1       0
Bank Sta=178,193
XS Rating Curve= 0 ,0
Exp/Cntr=0.3,0.1

Type RM Length L Ch R = 1 ,684.6   ,202.5,195.7,196.2
XS GIS Cut Line= 2
     1515444.898        437653.8     1515412.082      438222.609
#Sta/Elev= 30
      10   595.2      40  581.85      60  573.48      70  569.97      80  567.11
      90  563.37     100  557.45     110  552.28   119.9  549.53   129.9  548.44
   169.9  545.64   179.3  545.12   189.9  544.93   194.3  544.98   209.9  545.39
   229.9  546.37   249.9  547.59   279.9   549.7   289.9  550.26   299.9  550.56
   309.9  551.23   319.9  552.68   339.9  556.43   439.8  576.56   459.8  580.32
   469.8  581.81   479.8  582.86   489.8  583.61   549.8  587.35   569.8  589.23
#Mann= 3 , 0 , 0
       0      .1       0   179.3    .045       0   194.3      .1       0
Bank Sta=179.3,194.3
XS Rating Curve= 0 ,0
Exp/Cntr=0.3,0.1

Type RM Length L Ch R = 1 ,488.9   ,190.3,209.7,204.6
XS GIS Cut Line= 2
     1515273.527      437631.923     1515226.126       438076.76
#Sta/Elev= 30
     9.9  592.53    19.9  588.72    29.8  585.44    59.6   576.3    69.6   572.7
    79.5  568.76    89.5   565.3   109.4  558.87   129.2  551.58   139.2  549.28
   149.1  548.23   208.8  545.06   218.7   544.8   220.1  544.83   228.6  544.98
   235.1  545.52   248.5  547.03   258.5  548.78   268.4  552.62   278.4  559.65
   288.3   567.2   298.2   571.6   308.2  573.27     338   575.9   357.9  576.72
   367.8  576.85   387.7  576.52   417.5  576.88   427.5  576.57   447.4   575.2
#Mann= 3 , 0 , 0
       0      .1       0   220.1    .045       0   235.1      .1       0
Bank Sta=220.1,235.1
XS Rating Curve= 0 ,0
Exp/Cntr=0.3,0.1

Type RM Length L Ch R = 1 ,279.2   ,298.7,279.2,276.5
XS GIS Cut Line= 4
     1515219.818      437623.669     1515085.181       437750.02
     1515103.823      437913.655     1515203.247      438056.577
#Sta/Elev= 30
     9.7  587.61    48.6  578.37    58.3  575.55      68  572.03    97.2  559.11
   106.9  555.62   116.6  553.53   126.3  552.29   145.8     551   155.5  550.02
   174.9  545.95   183.3  544.68   184.6  544.49   194.3  544.49   198.3  545.08
   223.4  549.69   233.1  550.15   242.8  549.71   271.8  547.23   291.2  546.62
   349.3  547.15   378.4  547.74     388  548.51   397.7  549.53   407.4  551.83
     417  554.34   446.1  563.43   455.7  565.97   465.4  567.86   523.4  573.99
#Mann= 3 , 0 , 0
       0      .1       0   183.3    .045       0   198.3      .1       0
Bank Sta=183.3,198.3
XS Rating Curve= 0 ,0
Exp/Cntr=0.3,0.1

Chan Stop Cuts=-1
Use User Specified Reach Order=0